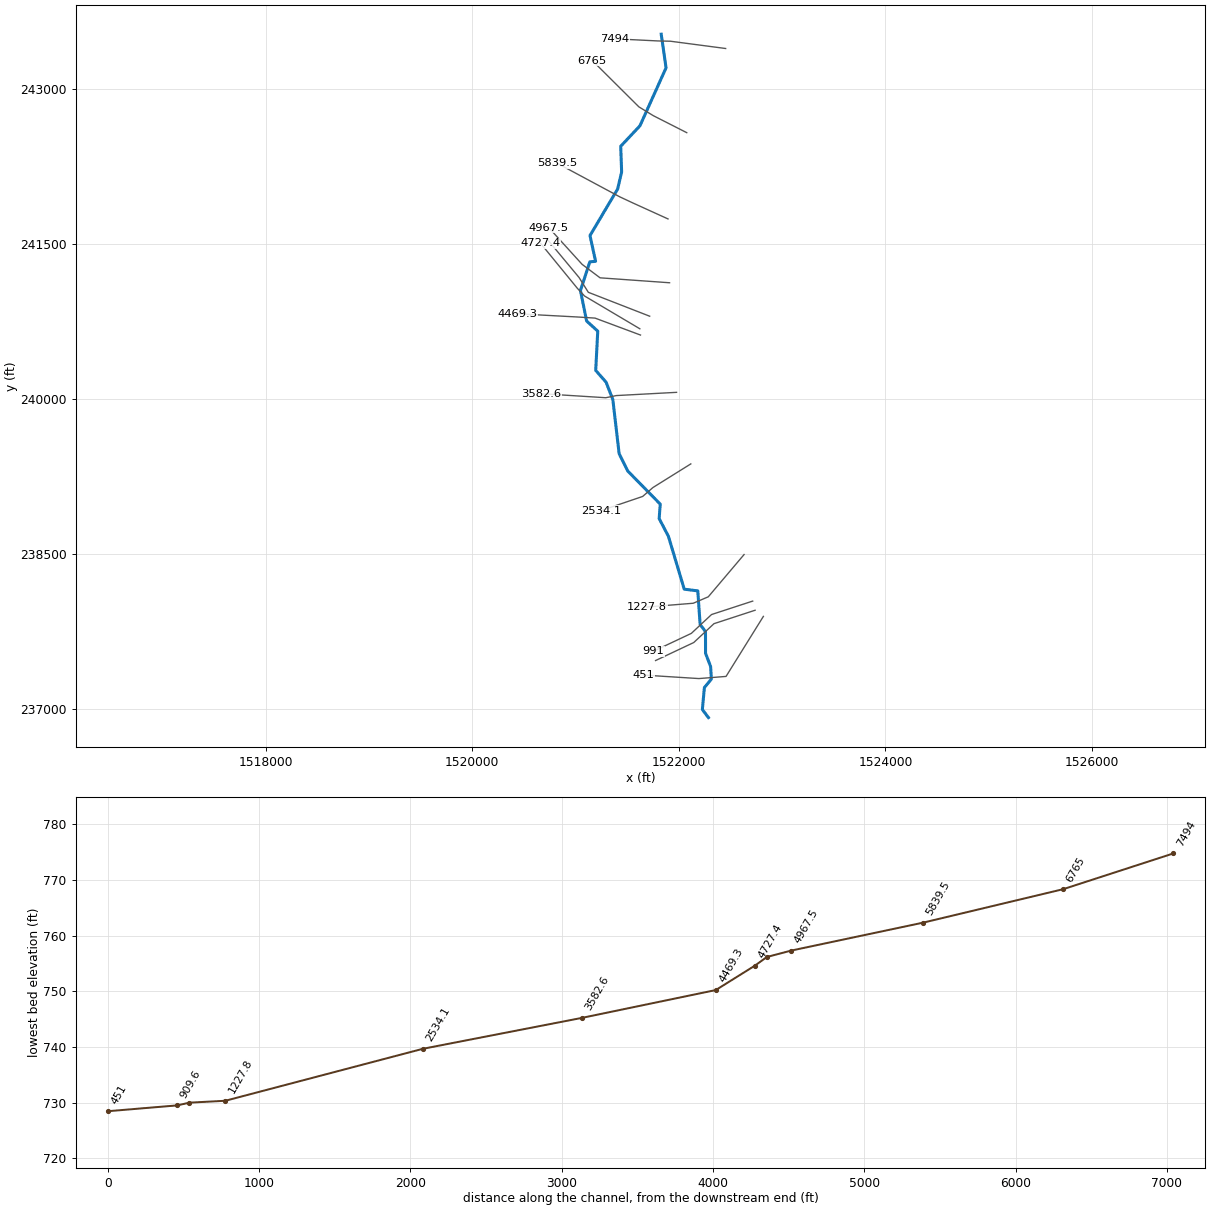
--- DGRN.prj (project) ---

Proj Title=DGRN
Current Plan=p01
Default Exp/Contr=0,0
English Units
Geom File=g01
Flow File=f01
Plan File=p01
BEGIN DESCRIPTION:
END DESCRIPTION:
DSS Export Rating Curves= 0
DSS Export Rating Curve Sorted= 0
DSS Export Volume Flow Curves= 0
DXF OffsetX= 0
DXF OffsetY= 0
DXF ScaleX= 0
DXF ScaleY= 0

--- DGRN.p01 (plan) ---

Plan Title=Floodplain
Program Version=4.00
Geom File=g01
Flow File=f01
K Sum by GR=0
Std Step Tol=0.01
Critical Tol=0.01
Num of Std Step Trials=20
Max Error Tol=0.3
Flow Tol Ratio=0.001
Split Flow NTrial=30
Split Flow Tol=0.02
Split Flow Ratio=0.02
Log Output Level=0
Friction Slope Method=1
Unsteady Friction Slope Method=2
Unsteady Bridges Friction Slope Method=1
Global Log Level=0
CheckData=False
Run HTab=0
Run UNet=0
Run PostProcess=0
UNET Theta=0
UNET Theta Warmup=0
UNET ZTol=0
UNET ZSATol=0
UNET MxIter=0
UNET MaxInSteps=0
UNET DtIC=0
UNET DtMin=0
UNET MaxCRTS=0
UNET WFStab=0
UNET SFStab=0
UNET WFX=0
UNET SFX=0
UNET DSS MLevel=0
UNET DZMax Abort=0
UNET Convert EG Bridges=0
UNET Use Existing IB Tables=0
UNET Froude Limit=0
UNET Froude Power=0
Write IC File=0
Echo Input=False
Echo Output=False
Write Detailed=0

--- DGRN.f01 (steady flow) ---

Flow Title=NFF Regression Equation
Program Version=4.10
Number of Profiles= 1
Profile Names=P100yr
River Rch & RM=DGRN,Main            ,7494
994.1336
River Rch & RM=DGRN,Main            ,4967.5
1040.681
River Rch & RM=DGRN,Main            ,4469.3
1133.494
River Rch & RM=DGRN,Main            ,451
1198.779
Boundary for River Rch & Prof#=DGRN,Main            , 1
Up Type= 0
Dn Type= 3
Dn Slope=0.00213
DSS Import GetInterval= 0
DSS Import GetPeak= 0
DSS Import FillOption= 0

--- DGRN.g01 (geometry) ---

Geom Title=USGS 10m DEM
Program Version=4.10

River Reach=DGRN            ,Main
Reach XY= 30
     1521829.628      243532.722     1521876.594      243206.746
     1521623.927      242645.654     1521437.697      242447.503
      1521446.54      242198.193     1521408.043      242033.804
      1521140.42      241583.154     1521194.239      241333.588
      1521138.52      241328.325     1521047.964      241050.839
     1521107.587       240755.57     1521215.422      240657.678
     1521195.623      240277.577     1521295.905      240163.758
      1521361.33       239995.53     1521422.279       239471.97
     1521506.282      239302.806     1521820.367      238983.106
     1521809.837      238843.569     1521899.468      238671.356
     1522052.684      238159.513     1522183.756      238143.144
     1522206.565      237817.284     1522258.408      237749.047
     1522258.842      237539.411     1522307.905      237410.893
     1522314.974      237289.658      1522247.81      237207.295
     1522228.054      236994.333      1522286.73        236916.9

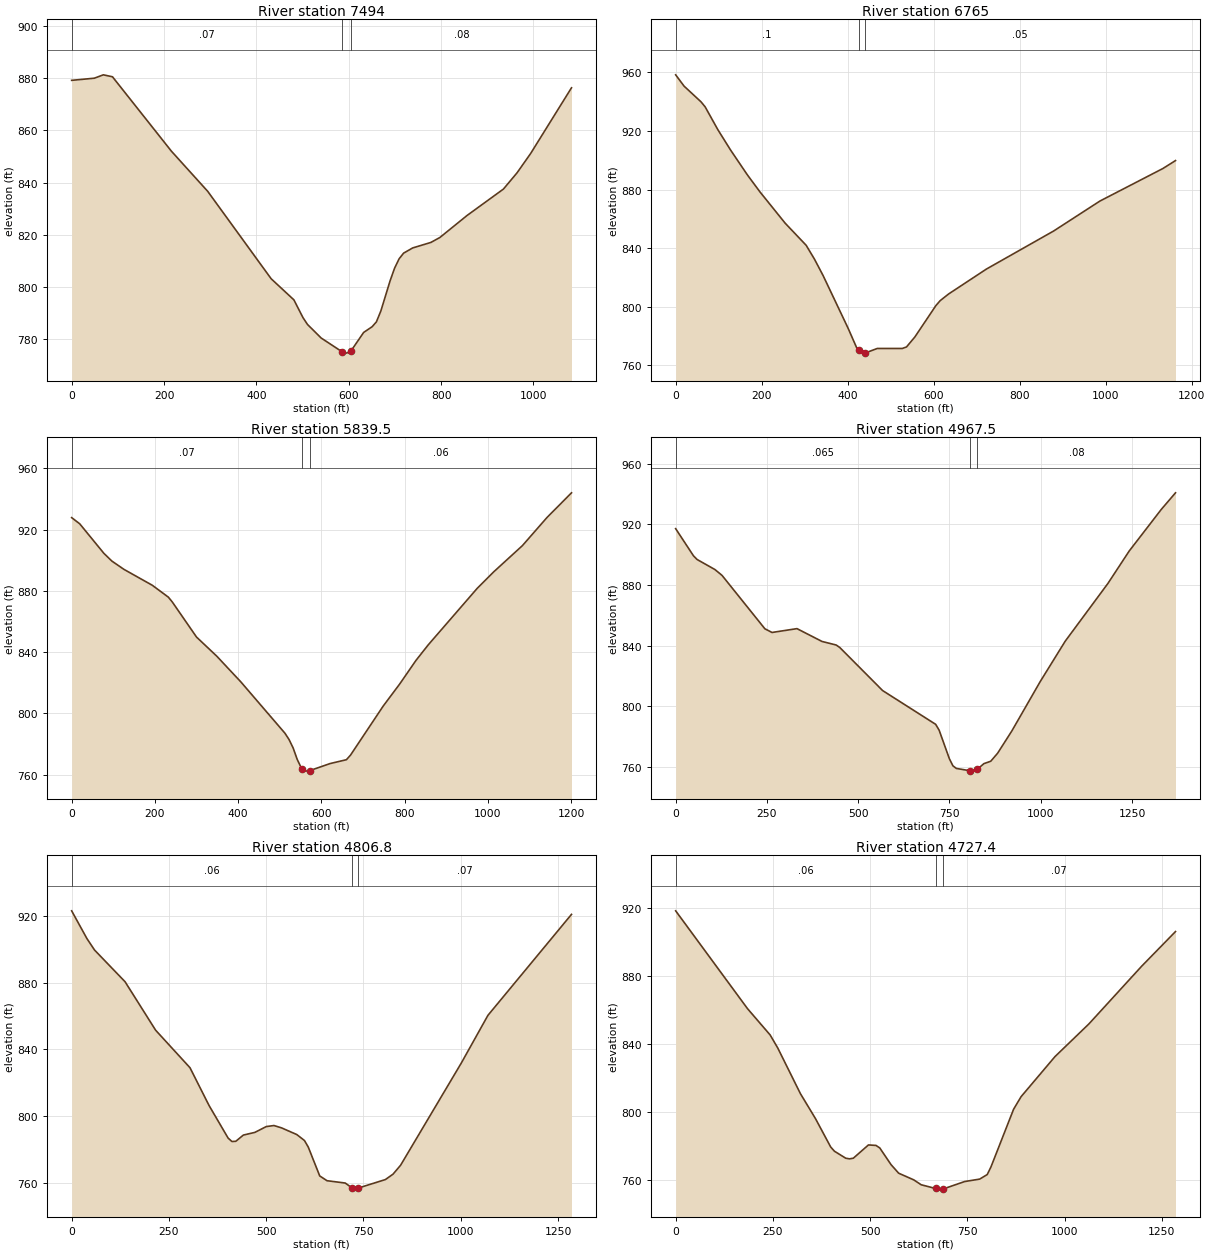
Type RM Length L Ch R = 1 ,7494    ,740.4,729.1,717.3
XS GIS Cut Line= 4
     1522453.569      243393.824     1521918.137      243464.399
     1521798.346      243467.003     1521376.471      243487.836
#Sta/Elev= 30
       0  879.06    49.1  879.88    68.7  881.17    88.4  880.42     216  851.98
   294.6  836.63     432   803.2   481.2  795.14   500.8  788.37   510.6  785.75
   540.1  780.57   586.2  775.21   595.4  774.77   605.3  775.72   632.2  782.67
   650.7  784.88   659.9  786.73   669.7  790.98   689.4  802.36   699.2  807.23
     709  810.82   718.8     813   738.5  814.99   777.8  817.09   797.4  818.99
   856.3  827.41   934.9  837.49   964.4   843.7   993.9  851.11  1082.3  876.21
#Mann= 3 , 0 , 0
       0     .07       0   586.2    .045       0   605.3     .08       0
Bank Sta=586.2,605.3
XS Rating Curve= 0 ,0
Exp/Cntr=0.3,0.1

Type RM Length L Ch R = 1 ,6765    ,920,925.4,925.4
XS GIS Cut Line= 4
     1522076.992      242578.982     1521754.075      242743.044
      1521613.45      242828.982     1521162.929      243276.899
#Sta/Elev= 30
       0  958.28    19.6  950.56    58.7  939.93    68.5  936.46    97.9  920.95
   127.3  907.13   166.4  890.15   195.8  878.47   254.5  857.07   303.5  841.92
     323  832.37   342.6  821.43     401  785.33   420.4  772.34   425.4  770.62
   430.1     769   439.8  768.34   440.4  768.39   468.8  771.52     527  771.53
   536.8  772.56   556.3   779.4   605.2  800.81     615  804.12   634.5  808.67
   722.5  825.69   878.9  851.68   986.4   872.1    1133  894.34  1162.3  899.74
#Mann= 3 , 0 , 0
       0      .1       0   425.4    .045       0   440.4     .05       0
Bank Sta=425.4,440.4
XS Rating Curve= 0 ,0
Exp/Cntr=0.3,0.1

Type RM Length L Ch R = 1 ,5839.5  ,869,872,860.1
XS GIS Cut Line= 4
     1521895.568      241743.912     1521551.818      241900.162
     1521429.422      241957.454     1520822.651      242282.975
#Sta/Elev= 30
       0  927.76    19.4  923.73    77.5  904.45    96.8  899.38   125.9  893.96
   193.6  883.66   232.4  875.87     242  872.67   300.1  849.83   348.6   837.4
   406.6  820.58   512.7  787.04   522.6   782.9   532.4  777.38   542.2  769.92
   552.9  763.85   561.9  762.33   571.8  762.62   620.9  767.25   660.3  769.78
   670.1  772.73   748.8  804.81   788.2  819.11   827.5  834.57     857  844.73
   975.1  881.73  1014.4  892.39  1083.3  909.48  1142.3  927.81  1201.3  943.95
#Mann= 3 , 0 , 0
       0     .07       0   552.9    .045       0   571.8     .06       0
Bank Sta=552.9,571.8
XS Rating Curve= 0 ,0
Exp/Cntr=0.3,0.1

Type RM Length L Ch R = 1 ,4967.5  ,168.8,160.6,150.8
XS GIS Cut Line= 4
       1521910.6      241126.074     1521237.857      241173.817
     1521064.246      241304.025     1520743.065      241657.758
#Sta/Elev= 30
       0  917.14    48.9  899.21    58.6  896.84   107.5   890.2   127.1  886.32
   244.4  851.14   263.9  848.71   332.3  851.24   400.8   842.8   439.8  840.43
   449.6   838.8   566.9  810.42   712.2  788.16   721.6  784.38   749.9  765.41
   759.4  760.83   768.8   759.1   806.5  757.55     816  757.31   826.1  758.47
   844.3  762.24   863.1  763.82     882  769.14   920.7  783.72   998.7  816.37
    1067  842.92    1184     881  1242.5  902.44  1330.2   929.8  1369.2  940.76
#Mann= 3 , 0 , 0
       0    .065       0   806.5    .045       0   826.1     .08       0
Bank Sta=806.5,826.1
XS Rating Curve= 0 ,0
Exp/Cntr=0.3,0.1

Type RM Length L Ch R = 1 ,4806.8  ,101.1,79.4,79.9
XS GIS Cut Line= 4
     1521718.224      240802.159     1521124.141      241033.626
     1521034.587       241176.71     1520728.641      241544.346
#Sta/Elev= 30
       0  923.08    39.2  906.45    58.8  899.57   137.3  880.54   215.8  851.49
   304.1  828.99   353.1  806.34   402.2  786.75     412  784.72   421.8  784.84
   441.4  788.59   470.8  790.18   500.3  793.69   519.9   794.3   539.5   792.9
   578.7  788.88   598.4  785.31   608.2  781.36   637.6  764.07   656.3  761.21
   703.2  759.81   721.5  756.75   731.4  756.16   736.5  756.79   806.4   761.9
   825.9  765.11   845.4  770.47  1001.6  831.83  1069.9  860.38  1284.7  920.95
#Mann= 3 , 0 , 0
       0     .06       0   721.5    .045       0   736.5     .07       0
Bank Sta=721.5,736.5
XS Rating Curve= 0 ,0
Exp/Cntr=0.3,0.1

Type RM Length L Ch R = 1 ,4727.4  ,214.7,258.1,279.9
XS GIS Cut Line= 4
     1521622.738      240680.631     1521087.755      240997.674
     1521018.354      241071.907     1520663.103      241506.586
#Sta/Elev= 30
       0  918.21   184.6  860.73   242.9  845.23   262.4   837.6   320.6  810.77
   359.5  796.03   398.4  779.42   408.1   776.9   437.2  772.77     447   772.4
   456.7  772.78   495.6  780.58     515  780.29   524.7  778.81   553.8  768.96
   573.3  763.96   612.2  760.03   631.1  757.17   668.1  754.98   686.5   754.6
   742.8  759.05   781.6   760.5   800.9  763.17   810.6  767.69   868.7  801.56
     888  808.96   975.2  832.53  1062.3  851.72  1197.8  885.62  1284.9  906.02
#Mann= 3 , 0 , 0
       0     .06       0   668.1    .045       0   686.5     .07       0
Bank Sta=668.1,686.5
XS Rating Curve= 0 ,0
Exp/Cntr=0.3,0.1

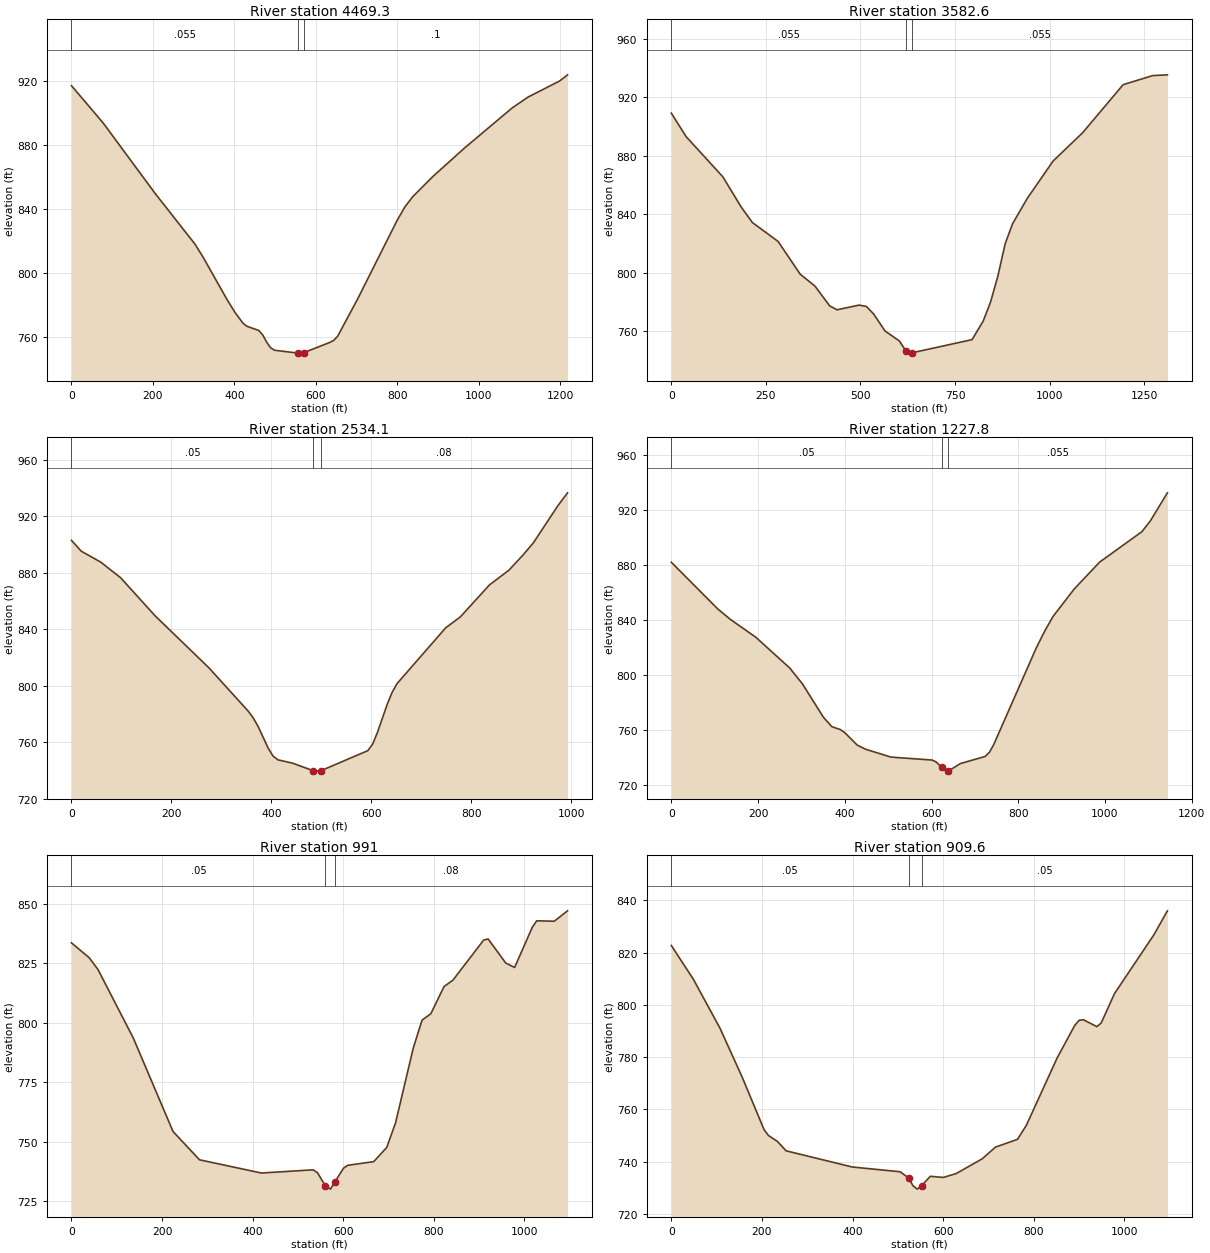
Type RM Length L Ch R = 1 ,4469.3  ,880,886.7,891.3
XS GIS Cut Line= 4
     1521629.249      240619.867     1521189.144       240783.93
     1521025.082      240794.346     1520441.749      240825.596
#Sta/Elev= 30
       0  917.01    78.3   893.6   205.5  849.78   303.3   818.2   322.9   810.2
   381.6  783.83   401.2  775.76   420.8     769   430.6  766.97   459.9  764.37
   469.7  761.56   479.4  757.03     489  753.56   498.7  752.02   556.3  750.23
   556.7  750.22   571.3  750.59   634.1  756.86   643.8  758.11   653.6  760.74
   702.2  783.72   799.6  832.94   819.1  841.52   838.5   847.9   887.2  860.29
   965.1  878.09    1082  903.07  1120.9  909.85  1198.8  919.92  1218.2  923.77
#Mann= 3 , 0 , 0
       0    .055       0   556.3    .045       0   571.3      .1       0
Bank Sta=556.3,571.3
XS Rating Curve= 0 ,0
Exp/Cntr=0.3,0.1

Type RM Length L Ch R = 1 ,3582.6  ,1036.4,1048.6,1058.8
XS GIS Cut Line= 4
     1521978.207       240065.18     1521394.874       240033.93
     1521293.311      240013.096     1520670.915      240052.159
#Sta/Elev= 30
       0  909.15    38.9  893.17   136.3  865.62     185  844.89   214.2  834.45
   282.4  821.46   340.8  799.09   379.7  791.02   418.7  777.49   438.1   774.8
   496.5  778.02     516  777.08   535.5  771.73   564.7  760.41     603  753.49
   620.3  746.68   631.3  745.21   635.3  745.37     795  754.41   824.3  766.98
   843.8  779.95   863.2  797.71   882.7  819.98   902.2  833.59   941.2  850.98
  1009.4  876.44  1087.4  895.75  1194.5  928.58  1272.5  934.78  1311.5  935.31
#Mann= 3 , 0 , 0
       0    .055       0   620.3    .045       0   635.3    .055       0
Bank Sta=620.3,635.3
XS Rating Curve= 0 ,0
Exp/Cntr=0.3,0.1

Type RM Length L Ch R = 1 ,2534.1  ,1310.4,1306.2,1295.2
XS GIS Cut Line= 4
     1522116.228      239372.471      1521749.04      239143.305
     1521650.082      239057.367     1521243.832      238919.346
#Sta/Elev= 30
       0  903.02    19.7  895.33      59  887.52    98.4  876.55   167.2   849.7
   275.4  812.69   354.1     782     364  777.25   373.8  771.17   393.5  756.15
   403.3  750.37   413.2  747.66   442.2  745.35     484  739.96     489  739.67
     499  739.92   593.2  754.15   602.9  758.78   612.6  767.18   632.2   787.1
   641.9  795.45   651.7  801.62   749.2  841.14   778.4  848.84   836.9  871.53
   875.9  881.97   905.2  893.16   924.7  901.32   973.4   927.4     993  936.66
#Mann= 3 , 0 , 0
       0     .05       0     484    .045       0     499     .08       0
Bank Sta=484,499
XS Rating Curve= 0 ,0
Exp/Cntr=0.3,0.1

Type RM Length L Ch R = 1 ,1227.8  ,226.5,236.8,244.5
XS GIS Cut Line= 4
     1522631.853      238494.867     1522285.499      238086.013
     1522139.665      238023.513     1521691.749      237987.055
#Sta/Elev= 30
       0  882.01   107.2  848.07   136.4  840.47   194.8  827.56   272.8  805.28
     302  793.84   350.7  769.47   370.2  762.58   389.7  760.52   399.4  758.44
   428.7  749.21   448.2   746.2   506.6  740.51   601.2  738.38   610.5  737.02
   623.1  733.27   638.1  730.38   638.5  730.33   666.5  735.82   723.8     741
   733.6  744.06   743.4  749.57     841  819.43   860.6  831.81   880.1  842.61
     929  862.57   987.6   882.1  1085.3  904.26  1104.8  912.16  1143.9  932.43
#Mann= 3 , 0 , 0
       0     .05       0   623.1    .045       0   638.1    .055       0
Bank Sta=623.1,638.1
XS Rating Curve= 0 ,0
Exp/Cntr=0.3,0.1

Type RM Length L Ch R = 1 ,991     ,83.2,81.4,82.2
XS GIS Cut Line= 4
     1522715.186      238044.346     1522316.749      237914.138
     1522121.436      237731.846     1521751.644      237557.367
#Sta/Elev= 30
       0  833.47      39  827.26    58.5  822.29   136.5  793.48   224.2  754.21
   282.7  742.31   419.2  736.76   533.7   738.1   543.2  736.86   560.1  731.51
   571.8  729.99   581.4  732.95   600.5  738.76     610     740   667.3  741.54
   696.1  747.51   715.6  757.91   754.5  789.18     774  800.98   793.4  803.71
   822.6  815.12   842.1  817.78   910.2  834.69     920  835.08   958.9  824.96
   978.4  823.13  1017.3  839.97  1027.1  842.74    1066  842.56  1095.2  846.93
#Mann= 3 , 0 , 0
       0     .05       0   560.1    .045       0   581.4     .08       0
Bank Sta=560.1,581.4
XS Rating Curve= 0 ,0
Exp/Cntr=0.3,0.1

Type RM Length L Ch R = 1 ,909.6   ,472.1,458.6,440
XS GIS Cut Line= 4
     1522738.624      237955.805     1522340.186      237825.596
     1522144.874      237643.305     1521775.082      237468.826
#Sta/Elev= 30
       0  822.71    48.7  809.77   107.2  791.15     156  772.52   204.7  752.27
   214.5     750     234  747.79   253.4  744.15   399.7  737.96     505  736.15
   523.7  733.81   533.7  730.75   543.2   729.5   552.8  730.84   571.8  734.41
   600.5  733.97   629.1  735.47   686.3  741.09   715.6  745.57   764.2  748.54
   783.7  753.86   851.8  779.69   890.8  792.17   900.5  794.11   910.2  794.27
   939.5  791.66   949.2   793.1   978.4   804.3    1066  826.96  1095.2  835.97
#Mann= 3 , 0 , 0
       0     .05       0   523.7     .04       0   552.8     .05       0
Bank Sta=523.7,552.8
XS Rating Curve= 0 ,0
Exp/Cntr=0.3,0.1

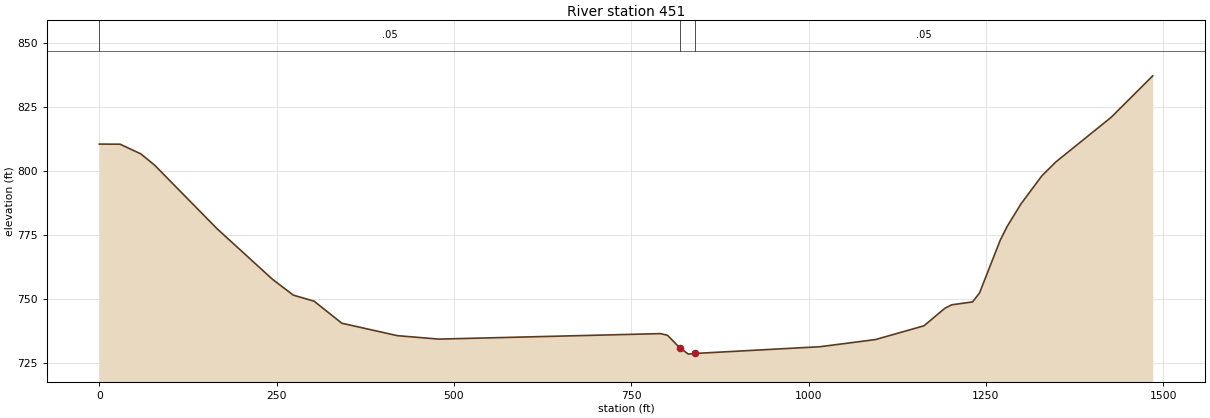
Type RM Length L Ch R = 1 ,451     ,431,451,467.8
XS GIS Cut Line= 4
     1522818.658      237896.039     1522457.374       237315.18
     1522194.353      237294.346     1521657.894      237328.201
#Sta/Elev= 30
       0  810.41    29.3  810.37    58.6  806.58    78.2  802.13   166.1  777.36
   244.3  757.62   273.6  751.47   302.9   749.1     342   740.5   420.2  735.66
   478.8  734.31   791.5  736.45   801.3  735.78   818.4  730.94   830.6  728.45
   840.4  728.72  1016.3  731.34  1094.5  734.14  1162.9  739.51  1192.2  746.33
    1202   747.7  1231.3  748.82  1241.1   752.3  1270.4  772.95  1280.2  778.31
  1299.7  787.12    1329     798  1348.6  803.41  1426.8  820.87  1485.4  837.05
#Mann= 3 , 0 , 0
       0     .05       0   818.4     .04       0   840.4     .05       0
Bank Sta=818.4,840.4
XS Rating Curve= 0 ,0
Exp/Cntr=0.3,0.1

Chan Stop Cuts=-1
Use User Specified Reach Order=0
Composite Channel Slope=5